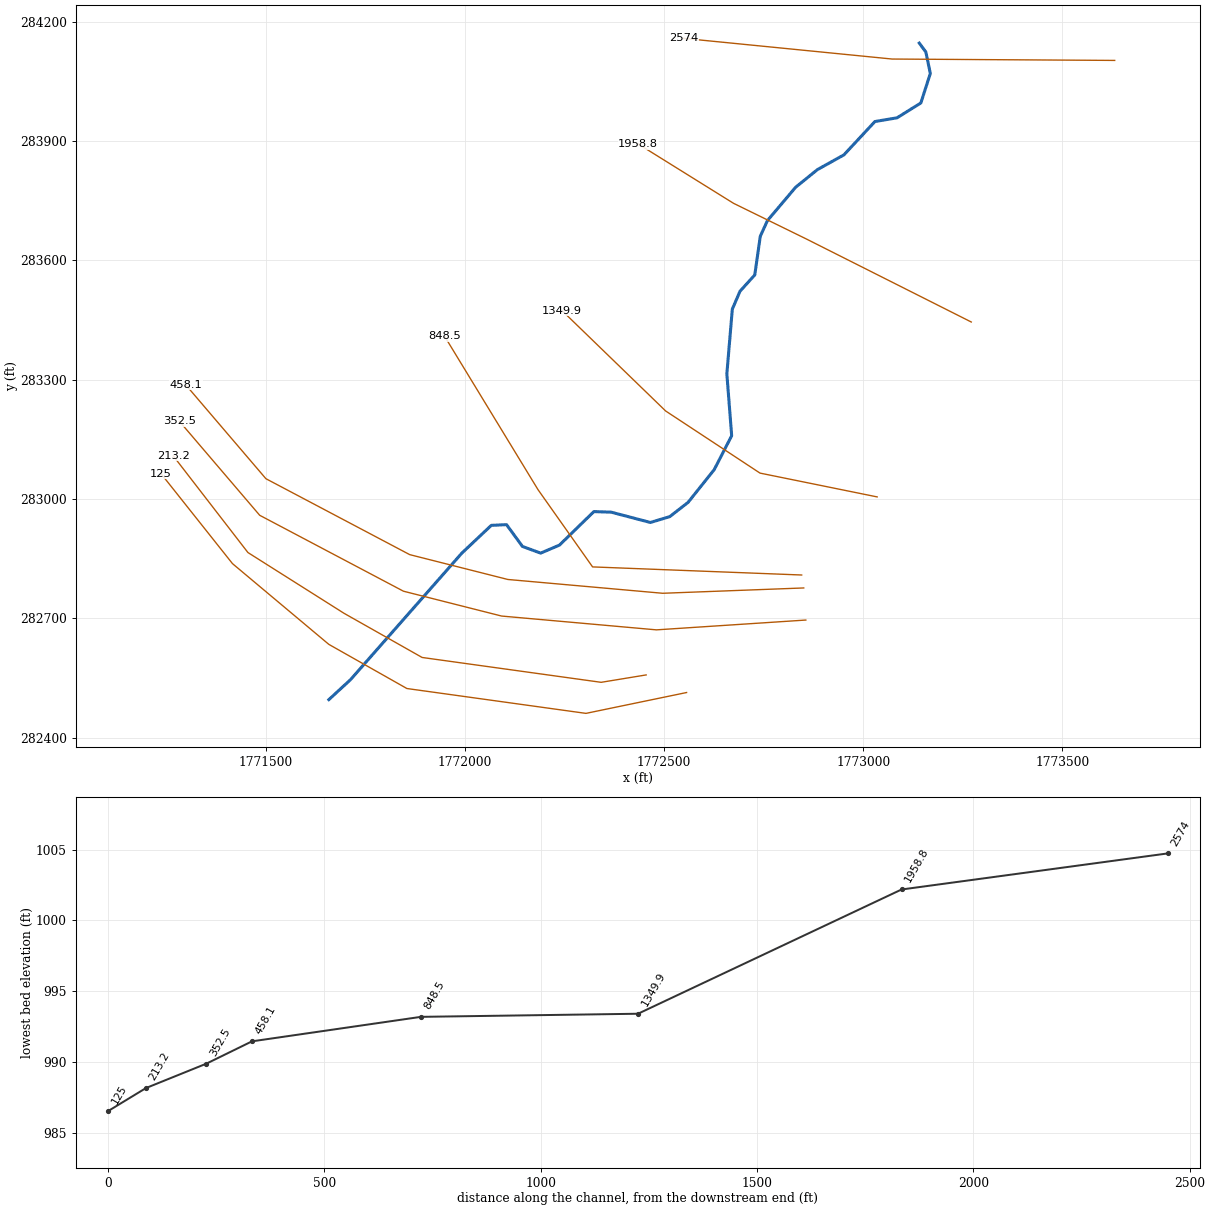
--- JerryRun.prj (project) ---

Proj Title=JerryRun
Current Plan=p01
Default Exp/Contr=0,0
English Units
Geom File=g01
Flow File=f01
Plan File=p01
BEGIN DESCRIPTION:
END DESCRIPTION:
DSS Export Rating Curves= 0
DSS Export Rating Curve Sorted= 0
DSS Export Volume Flow Curves= 0
DXF OffsetX= 0
DXF OffsetY= 0
DXF ScaleX= 0
DXF ScaleY= 0

--- JerryRun.p01 (plan) ---

Plan Title=Floodplain
Program Version=4.00
Geom File=g01
Flow File=f01
K Sum by GR=0
Std Step Tol=0.01
Critical Tol=0.01
Num of Std Step Trials=20
Max Error Tol=0.3
Flow Tol Ratio=0.001
Split Flow NTrial=30
Split Flow Tol=0.02
Split Flow Ratio=0.02
Log Output Level=0
Friction Slope Method=1
Unsteady Friction Slope Method=2
Unsteady Bridges Friction Slope Method=1
Global Log Level=0
CheckData=False
Run HTab=0
Run UNet=0
Run PostProcess=0
UNET Theta=0
UNET Theta Warmup=0
UNET ZTol=0
UNET ZSATol=0
UNET MxIter=0
UNET MaxInSteps=0
UNET DtIC=0
UNET DtMin=0
UNET MaxCRTS=0
UNET WFStab=0
UNET SFStab=0
UNET WFX=0
UNET SFX=0
UNET DSS MLevel=0
UNET DZMax Abort=0
UNET Convert EG Bridges=0
UNET Use Existing IB Tables=0
UNET Froude Limit=0
UNET Froude Power=0
Write IC File=0
Echo Input=False
Echo Output=False
Write Detailed=0

--- JerryRun.f01 (steady flow) ---

Flow Title=NFF Regression Equation
Program Version=4.10
Number of Profiles= 1
Profile Names=P100yr
River Rch & RM=JerryRun,Main            ,2574
     889
River Rch & RM=JerryRun,Main            ,213.2
     930
Boundary for River Rch & Prof#=JerryRun,Main            , 1
Up Type= 0
Dn Type= 3
Dn Slope=0.019
DSS Import GetInterval= 0
DSS Import GetPeak= 0
DSS Import FillOption= 0

--- JerryRun.g01 (geometry) ---

Geom Title=USGS 10m DEM
Program Version=4.10

River Reach=JerryRun        ,Main
Reach XY= 30
     1773140.504      284146.696      1773157.05      284124.376
     1773168.309      284070.345     1773144.494      283996.056
     1773084.822      283958.837     1773029.084      283949.343
     1772951.268      283865.531     1772884.649      283828.427
      1772830.07      283784.176       1772759.2      283700.249
     1772741.172      283660.601     1772727.399      283563.565
     1772690.242      283522.498      1772670.96      283477.545
     1772657.258      283314.622     1772669.355      283159.116
     1772625.461      283073.725     1772559.829      282991.447
     1772514.076      282955.734     1772465.197      282940.915
     1772366.627      282966.871       1772323.3      282968.296
     1772236.719      282883.925      1772189.49      282863.868
     1772143.791      282880.694     1772103.906      282935.461
     1772065.596      282933.666     1771991.483      282863.687
     1771711.762      282545.281     1771657.609      282495.377

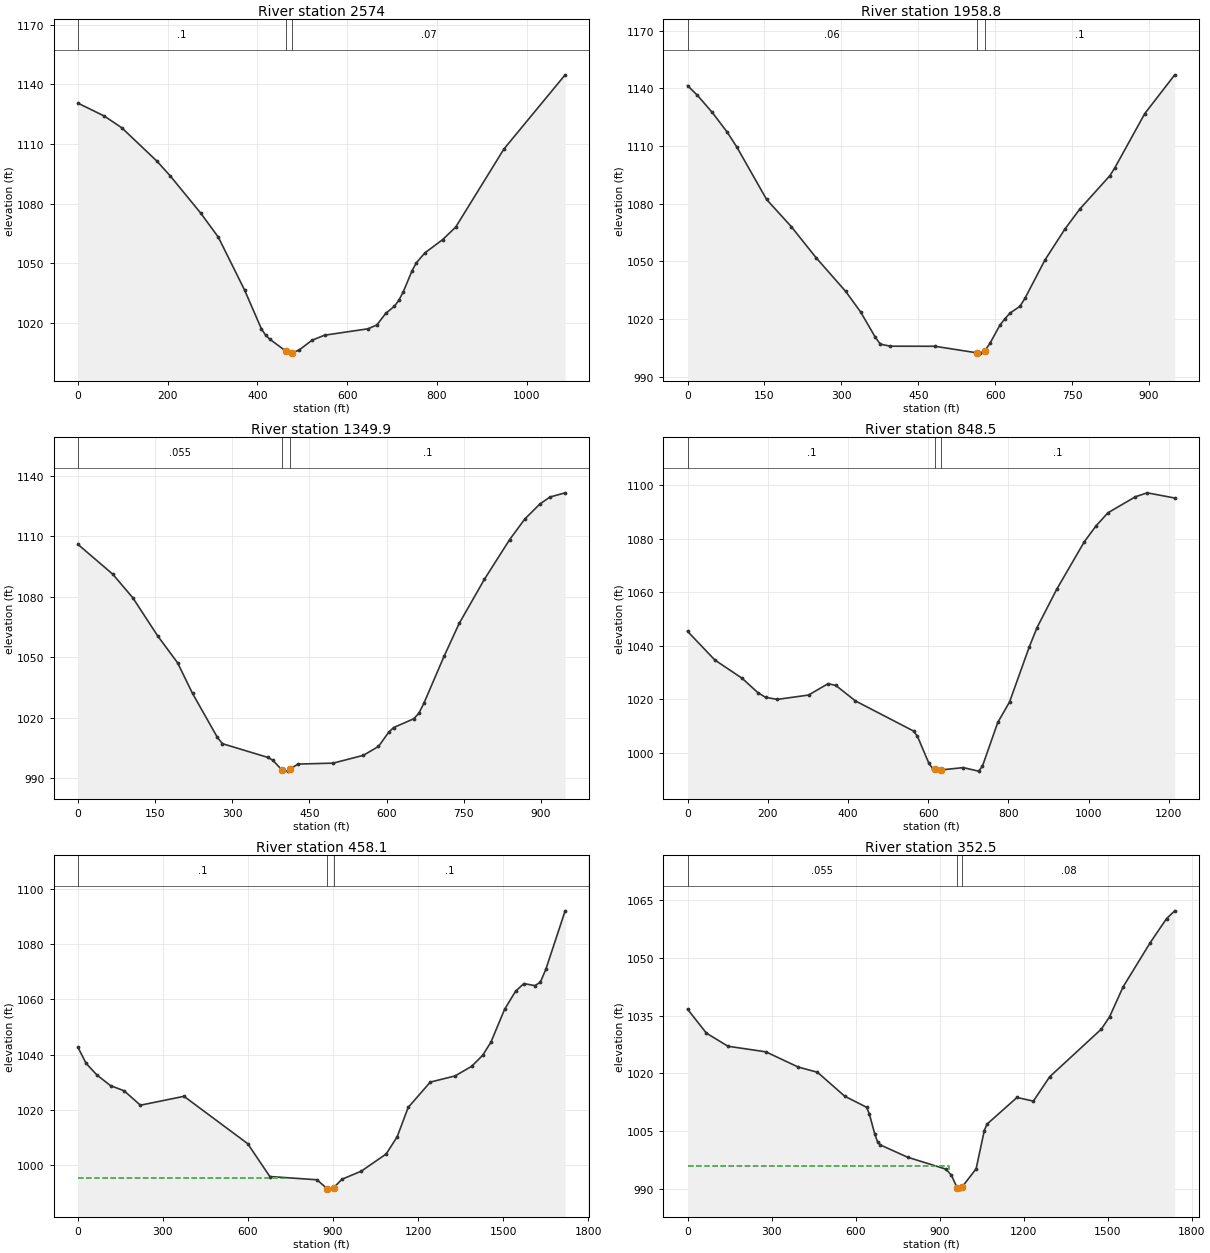
Type RM Length L Ch R = 1 ,2574    ,625.1,615.2,604.8
XS GIS Cut Line= 4
     1773631.448      284103.119     1773259.934      284105.427
      1773072.42      284106.592     1772548.115      284158.675
#Sta/Elev= 30
       0 1130.51    58.7 1124.03    97.8 1118.11     176 1101.35   205.3 1094.03
   273.8 1075.15   312.9  1063.1   371.5 1036.45     409 1016.94   418.4 1013.75
   427.8 1011.72   463.1 1005.82   474.7 1004.73   478.1 1004.84   493.4 1006.36
   521.5 1011.18   549.7 1013.75   646.8 1016.98   666.4 1018.92   685.9 1024.69
   705.4 1028.32   715.2 1031.35   724.9 1035.45   744.4    1046   754.2 1050.16
   773.7 1055.24   812.7  1061.8     842 1068.14   949.3 1107.38  1085.9 1144.75
#Mann= 3 , 0 , 0
       0      .1       0   463.1    .045       0   478.1     .07       0
Bank Sta=463.1,478.1
XS Rating Curve= 0 ,0
Exp/Cntr=0.3,0.1

Type RM Length L Ch R = 1 ,1958.8  ,611.9,608.9,605.9
XS GIS Cut Line= 4
     1773271.205      283445.133      1772858.01      283653.467
     1772673.983      283743.744     1772434.399       283893.05
#Sta/Elev= 30
       0 1141.36    19.3 1136.31    48.2 1127.41    77.1 1117.26    96.4 1109.29
   154.2 1082.13   202.4 1067.98   250.6 1051.86   308.5 1034.27   337.4 1023.66
   366.3 1010.39     376 1006.86   395.3 1005.79   482.3 1005.75   564.2 1002.34
   570.1 1002.18   579.2 1003.27   589.6  1007.2   609.2 1016.78   618.9 1020.07
   628.7 1022.98   648.2 1026.54     658  1030.7   696.9 1050.63   735.9 1066.73
   765.1 1077.19   823.5 1094.49   833.2 1098.58   891.6 1126.81     950 1146.96
#Mann= 3 , 0 , 0
       0     .06       0   564.2    .045       0   579.2      .1       0
Bank Sta=564.2,579.2
XS Rating Curve= 0 ,0
Exp/Cntr=0.3,0.1

Type RM Length L Ch R = 1 ,1349.9  ,509.4,501.5,492.4
XS GIS Cut Line= 4
     1773034.747      283005.232     1772740.476      283065.128
     1772503.497      283221.378      1772243.08      283473.982
#Sta/Elev= 30
       0 1105.95    67.8 1091.12   106.6 1079.47     155 1060.53   193.7 1047.19
   222.8 1031.95   271.2 1010.11   280.9 1007.03   368.8 1000.24   378.6  998.85
   396.7  993.96     408   993.4   411.7  994.27   427.6   996.9   496.1  997.37
   554.8 1001.25   584.2 1005.64   603.8 1012.61   613.6 1015.02   652.8 1019.38
   662.6 1022.12   672.4 1027.05   711.6 1050.35     741 1066.67   790.1 1088.61
   839.1 1108.28   868.5 1118.48   897.9 1125.96   917.5 1129.42     947 1131.51
#Mann= 3 , 0 , 0
       0    .055       0   396.7    .045       0   411.7      .1       0
Bank Sta=396.7,411.7
XS Rating Curve= 0 ,0
Exp/Cntr=0.3,0.1

Type RM Length L Ch R = 1 ,848.5   ,372.6,390.4,406.8
XS GIS Cut Line= 4
     1772845.207      282808.791      1772319.99      282829.161
     1772182.837      283023.606     1771948.462      283409.022
#Sta/Elev= 30
       0 1045.43    68.1  1034.7   136.3 1027.85   175.2 1022.53   194.7 1020.74
   223.9 1019.98   301.7  1021.6   350.4 1025.85   369.9 1025.18   418.5 1019.42
   563.7 1008.14   573.2  1006.2   601.8  996.08   611.3  994.13   617.1  993.79
   632.1  993.63   687.4  994.49   725.5  993.18     735  994.93   773.4 1011.36
   802.8 1019.02   851.8 1039.52   871.4 1046.83   920.5 1061.15   989.1 1078.85
  1018.5 1084.82  1047.9 1089.67  1116.6 1095.69    1146 1097.15  1214.6 1095.21
#Mann= 3 , 0 , 0
       0      .1       0   617.1    .045       0   632.1      .1       0
Bank Sta=617.1,632.1
XS Rating Curve= 0 ,0
Exp/Cntr=0.3,0.1

Type RM Length L Ch R = 1 ,458.1   ,105.8,105.6,105.5
XS GIS Cut Line= 6
     1772850.415      282776.239     1772496.031      282762.842
     1772107.142      282797.564     1771860.615      282860.064
     1771499.503      283051.036     1771298.115      283287.147
#Sta/Elev= 30
       0 1042.71    28.8 1036.89    67.1 1032.67     115 1028.83   162.9 1026.97
   220.4 1021.76   374.2 1024.97   598.7 1007.88   676.8     996   842.9  994.83
  879.34  991.59     882  991.45   901.6  991.93   930.9  995.01   999.4  997.94
  1086.9 1004.13  1125.8 1010.33  1164.7 1020.95  1242.6  1030.1  1330.1 1032.33
  1388.4  1035.8  1427.3 1039.77  1456.4 1044.52  1504.9 1056.43  1543.7 1062.96
  1572.8 1065.69  1611.6 1064.94    1631 1066.21  1650.4 1070.92  1718.2 1091.96
#Mann= 3 , 0 , 0
       0      .1       0  879.34    .045       0   901.6      .1       0
#XS Ineff= 2 , 0
          744.85  995.53
Permanent Ineff=
       F       F
Bank Sta=879.34,901.6
XS Rating Curve= 0 ,0
Exp/Cntr=0.3,0.1

Type RM Length L Ch R = 1 ,352.5   ,145.9,139.3,132.6
XS GIS Cut Line= 6
     1772855.623      282695.509     1772480.406      282670.828
     1772091.517       282705.55      1771844.99       282768.05
     1771483.878      282959.022      1771282.49      283195.133
#Sta/Elev= 30
       0  1036.7    67.5 1030.45   144.6 1027.04   279.6 1025.59   395.6 1021.62
   463.9 1020.28   561.5 1014.04   639.6 1011.16   649.3 1009.42   668.8 1004.14
   678.6 1002.18   688.4 1001.37     786  998.17     923  995.06   942.5  993.47
   962.3  990.26   971.9  989.87   981.7  990.55  1030.5  995.17  1059.7 1005.12
  1069.4 1006.78  1176.4 1013.72  1234.8 1012.76  1293.1  1019.1  1477.8 1031.52
  1506.9  1034.7  1555.4 1042.51  1652.3 1054.02  1710.5 1060.26  1739.6 1062.27
#Mann= 3 , 0 , 0
       0    .055       0   962.3    .045       0   981.7     .08       0
#XS Ineff= 2 , 0
          933.67  995.81
Permanent Ineff=
       F       F
Bank Sta=962.3,981.7
XS Rating Curve= 0 ,0
Exp/Cntr=0.3,0.1

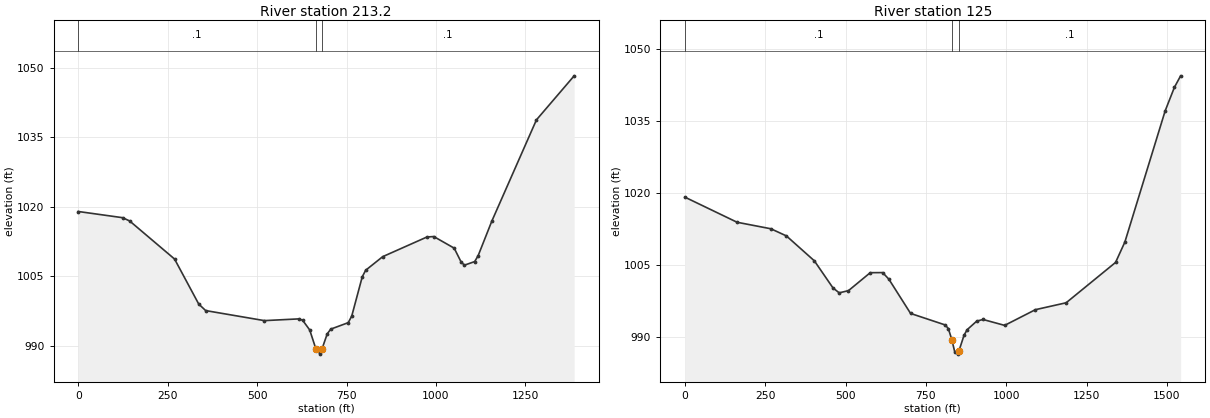
Type RM Length L Ch R = 1 ,213.2   ,88.1,88.2,88.1
XS GIS Cut Line= 6
     1772454.582      282557.489     1772341.517      282538.883
     1771891.865      282601.383     1771695.684      282712.494
     1771454.365      282865.272     1771266.865      283108.328
#Sta/Elev= 30
       0 1018.97   124.2 1017.63   143.6 1016.92   269.1  1008.7   336.7  998.97
   356.1  997.56   520.3  995.39   617.6  995.77   627.4  995.46     647  993.38
  664.68   989.2   676.4  988.15   681.8  989.35     696  992.52   705.8  993.55
   754.8  994.95   764.6  996.37     794 1004.86   803.5 1006.27   851.1 1009.21
   974.9 1013.46     994 1013.56  1051.1 1011.05  1070.1 1008.12  1079.6 1007.37
  1108.4 1008.15    1118 1009.41  1156.4  1016.9  1281.1 1038.77  1386.6 1048.29
#Mann= 3 , 0 , 0
       0      .1       0  664.68    .045       0   681.8      .1       0
Bank Sta=664.68,681.8
XS Rating Curve= 0 ,0
Exp/Cntr=0.3,0.1

Type RM Length L Ch R = 1 ,125     ,132.2,125,118.1
XS GIS Cut Line= 6
     1772556.144      282513.218     1772303.323      282460.758
      1771853.67      282523.258      1771657.49      282634.369
     1771415.519      282837.437     1771235.832      283063.999
#Sta/Elev= 30
       0 1019.23   162.6 1013.99   267.9 1012.63   316.2 1011.14   403.1 1005.95
     461 1000.31   480.4  999.28   509.3  999.74     577 1003.48   615.6  1003.5
   634.9 1002.13   702.5  994.99   810.2  992.59     820  991.83   831.1  989.46
   839.6  987.05   849.4  986.51  852.54  987.09     869  990.48   878.8  991.62
   908.2  993.38   927.8  993.73   995.1   992.5  1090.8  995.77  1186.5  997.21
  1340.3 1005.62  1369.2 1009.86  1494.5 1037.18  1523.4 1042.11  1542.7  1044.5
#Mann= 3 , 0 , 0
       0      .1       0   831.1    .045       0  852.54      .1       0
Bank Sta=831.1,852.54
XS Rating Curve= 0 ,0
Exp/Cntr=0.3,0.1

Chan Stop Cuts=-1
Use User Specified Reach Order=0
Composite Channel Slope=5